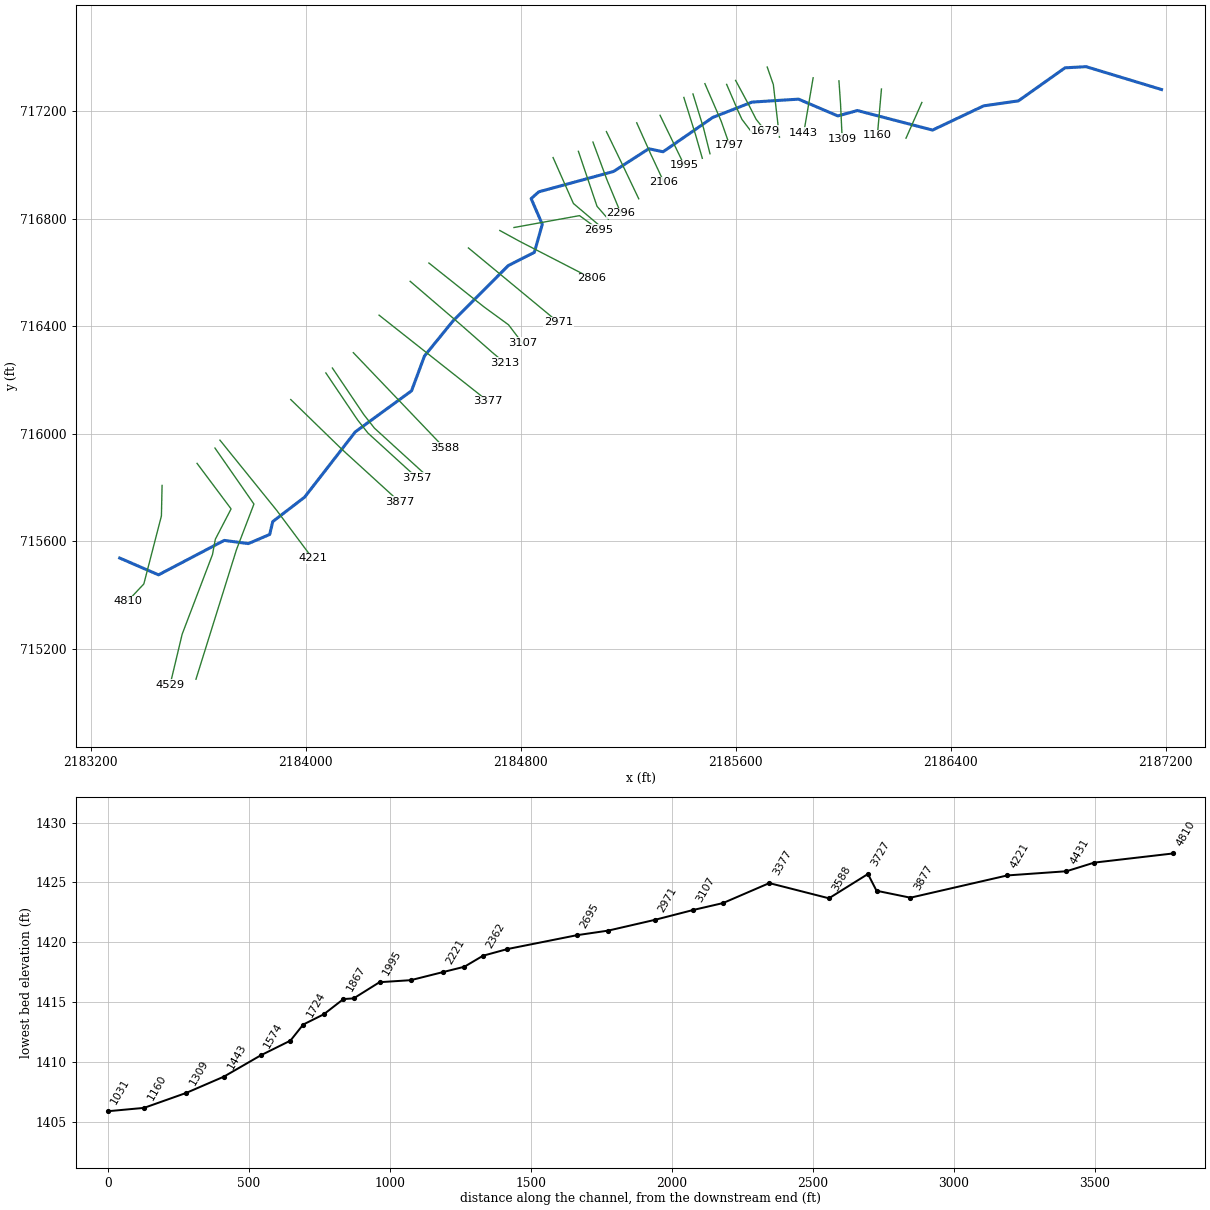
--- STONYRN.prj (project) ---

Proj Title=STONYRN
Current Plan=p01
Default Exp/Contr=0,0
English Units
Geom File=g01
Flow File=f01
Plan File=p01
BEGIN DESCRIPTION:
-------- MODELED AS PART OF WVEMD CTP PROGRAM, 2023----------
Stream Name: Stony Run
Flood Zone:  AFH
Upshur County, WV
HEC-RAS Version: RAS 6.3
Vertical Datum: NAVD88
Projection: NAD 1983 StatePlane West Virginia S FIPS 4702 (US Feet)
Terrain: 1-meter LIDAR (FEMA Region III 3DEP collected 2016-2018)
Land Use: 2019 NLCD
Hydrologic Method:
WV SIR2010-5033 regression equations
Additional Model Notes:
None
END DESCRIPTION:
DSS Export Rating Curves= 0
DSS Export Rating Curve Sorted= 0
DSS Export Volume Flow Curves= 0
DXF OffsetX= 0
DXF OffsetY= 0
DXF ScaleX= 0
DXF ScaleY= 0

--- STONYRN.p01 (plan) ---

Plan Title=Floodplain
Program Version=6.30
Short Identifier=Floodplain
Geom File=g01
Flow File=f01
Subcritical Flow
K Sum by GR= 0
Std Step Tol= 0.01
Critical Tol= 0.01
Num of Std Step Trials= 20
Max Error Tol= 0.3
Flow Tol Ratio= 0.001
Split Flow NTrial= 30
Split Flow Tol= 0.02
Split Flow Ratio= 0.02
Log Output Level= 0
Friction Slope Method= 1
Unsteady Friction Slope Method= 2
Unsteady Bridges Friction Slope Method= 1
Parabolic Critical Depth
Global Vel Dist= 0 , 0 , 0
Global Log Level= 0
CheckData=True
Encroach Param=-1 ,0,0, 0
Mapping Interval=1HOUR
Computation Time Step Use Courant=        0
Computation Time Step Use Time Series=    0
Computation Time Step Count To Double=0
Computation Time Step Max Doubling=0
Computation Time Step Max Halving=0
Computation Time Step Residence Courant=0
Run HTab= 0
Run UNet= 0
Run Sediment= 0
Run PostProcess= 0
Run WQNet= 0
Run RASMapper= 0
UNET Theta= 0
UNET Theta Warmup= 0
UNET ZTol= 0
UNET ZSATol= 0
UNET MxIter= 0
UNET Max Iter WO Improvement= 0
UNET MaxInSteps= 0
UNET DtIC= 0
UNET DtMin= 0
UNET MaxCRTS= 0
UNET WFStab= 0
UNET SFStab= 0
UNET WFX= 1
UNET SFX= 1
UNET Gravity=32.17405
UNET 1D Methodology=Finite Difference
UNET DSS MLevel= 1
UNET Pardiso=0
UNET DZMax Abort= 0
UNET Use Existing IB Tables= 0
UNET Froude Reduction=False
UNET Froude Limit= 0
UNET Froude Power= 0
UNET D1 Cores= 0
UNET WindReference=Eulerian
UNET WindDragFormulation=Hsu (1988)
UNET D2 Coriolis=0
UNET D2 Cores= 0
UNET D2 Theta= 1
UNET D2 Theta Warmup= 1
UNET D2 Z Tol= 0.01
UNET D2 Volume Tol= 0.01
UNET D2 Max Iterations= 20
UNET D2 Equation= 0
UNET D2 RampUpFraction=0.1
UNET D2 TimeSlices= 1
UNET D2 Turbulence Formulation=Non-Conservative (original)
UNET D2 Eddy Viscosity=0.3
UNET D2 Transverse Eddy Viscosity=0.1
UNET D2 Smagorinsky Mixing=0
UNET D2 BCVolumeCheck=0
UNET D2 Cores=0
UNET D2 SolverType=PARDISO (Direct)
UNET D2 Minimum Iterations= 3
UNET D2 Maximum Iterations= 30
UNET D2 Restart Number= 10
UNET D2 Relaxation Coeff=1.3
UNET D2 SOR Precondition Iterations= 10
UNET D2 ILUT Maximum Fill= 8
UNET D2 ILUT Tolerance=1E-08
UNET D2 Convergence Tolerance=0.00001
UNET D1D2 MaxIter= 0
UNET D1D2 ZTol=0.01
UNET D1D2 QTol=0.1
UNET D1D2 MinQTol=1
Write IC File= 0
Write IC File at Fixed DateTime=0
Write IC File at Sim End=0
Echo Input=False
Echo Parameters=False
Echo Output=False
Write Detailed= 0
HDF Write Warmup=0
HDF Write Time Slices=0
HDF Flush=0
HDF Compression= 1
HDF Chunk Size= 1
HDF Spatial Parts= 1
HDF Use Max Rows=0
HDF Fixed Rows= 1
Calibration Method= 0
Calibration Iterations= 20
Calibration Max Change=0.05
Calibration Tolerance=0.2
Calibration Maximum=1.5
Calibration Minimum=0.5
Calibration Optimization Method= 1
WQ AD Non Conservative
WQ ULTIMATE=-1
WQ Max Comp Step=1HOUR
WQ Output Interval=15MIN
WQ Output Selected Increments= 0
WQ Output face flow=0
WQ Output face velocity=0
WQ Output face area=0
WQ Output face dispersion=0
WQ Output cell volume=0
WQ Output cell surface area=0
WQ Output cell continuity=0
WQ Output cumulative cell continuity=0
WQ Output face conc=0
WQ Output face dconc_dx=0
WQ Output face courant=0
WQ Output face peclet=0
WQ Output face adv mass=0
WQ Output face disp mass=0
WQ Output cell mass=0
WQ Output cell source sink temp=0
WQ Output nsm pathways=0
WQ Output nsm derived pathways=0
WQ Create Restart=0
WQ Fixed Restart=0
WQ System Summary=0
WQ Write To DSS=0
Sorting and Armoring Iterations= 10
XS Update Threshold= 0.02
Bed Roughness Predictor= 0
Hydraulics Update Threshold= 0.02
Energy Slope Method= 1
Volume Change Method= 1
Sediment Retention Method= 0
Sediment TS Multiplier= 1
Warm Up Method= 0
XS Weighting Method= 0
Number of US Weighted Cross Sections= 1
Number of DS Weighted Cross Sections= 1
Upstream XS Weight=0
Main XS Weight=1
Downstream XS Weight=0
Number of DS XS's Weighted with US Boundary= 1
Upstream Boundary Weight= 1
Weight of XSs Associated with US Boundary= 0
Number of US XS's Weighted with DS Boundary= 1
Downstream Boundary Weight= 0.5
Weight of XSs Associated with DS Boundary= 0.5
Percentile Method= 0
Sediment Output Level= 3
Mass or Volume Output= 0
Output Increment Type= 1
Profile and TS Output Increment= 1
Transport Output Increment 1
XS Output Flag= 0
XS Output Increment= 10
Read HDF5 Sediment Hotstart= 0
Sediment Hotstart Type= 0
Write Gradation File= 0
Read Gradation Hotstart= 0
Write HDF5 File= 1
Write Binary Output= 1
Write DSS Sediment File= 0
DSS Sediment Output Type= 1
SV Curve= 0
Specific Gage Flag= 0
Subcell Erosion Methods= 0
Subcell Deposition Methods= 0
Advection Scheme= 1
Matrix Solver= 0
Implicit Weighting Factor= 1
Maximum Outer Loop Convergence Iterations= 5
Convergence Maximum Absolute= 0.001
Convergence RMSE= 0.0001
Grain Fractions Max Abs Error= 0.001
Max Subgrid Regions= 1
Max Subgrid Length Scale= 3.402823E+38
Initial Layer Thickness= 3.402823E+38
Min Layer Thickness= 3.402823E+38
Max Layer Thickness= 3.402823E+38
Number of Layers= 5

--- STONYRN.f01 (steady flow) ---

Flow Title=Flows
Program Version=6.30
Number of Profiles= 1
Profile Names=01pct
River Rch & RM=STONYRN,Main            ,4810
     346
River Rch & RM=STONYRN,Main            ,4431
     393
River Rch & RM=STONYRN,Main            ,1995
     439
Boundary for River Rch & Prof#=STONYRN,Main            , 1
Up Type= 0
Dn Type= 3
Dn Slope=0.00866
DSS Import GetInterval= 0
DSS Import GetPeak= 0
DSS Import FillOption= 0

--- STONYRN.g01 (geometry) ---

Geom Title=Geometry
Program Version=6.30

River Reach=STONYRN         ,Main
Reach XY= 30
     2183307.596      715538.522     2183452.138       715475.91
2183696.65756378715604.098767914     2183786.148      715592.149
     2183865.759      715626.174     2183877.263      715674.221
     2183995.849      715765.107     2184184.345      716008.003
     2184393.617      716160.643      2184441.75      716290.303
     2184547.258      716420.022     2184753.125      716626.403
     2184850.621      716675.995     2184880.038      716780.159
     2184838.573      716875.795      2184867.19      716901.149
     2185145.083      716976.782     2185276.289      717061.429
     2185329.573      717050.097     2185514.177      717177.812
     2185660.522       717234.93     2185833.479      717245.919
      2185979.68      717183.507     2186052.652       717203.51
      2186332.12      717130.853     2186522.304      717220.937
     2186651.708      717239.595     2186825.066      717362.445
     2186903.446      717366.766     2187184.173      717281.718

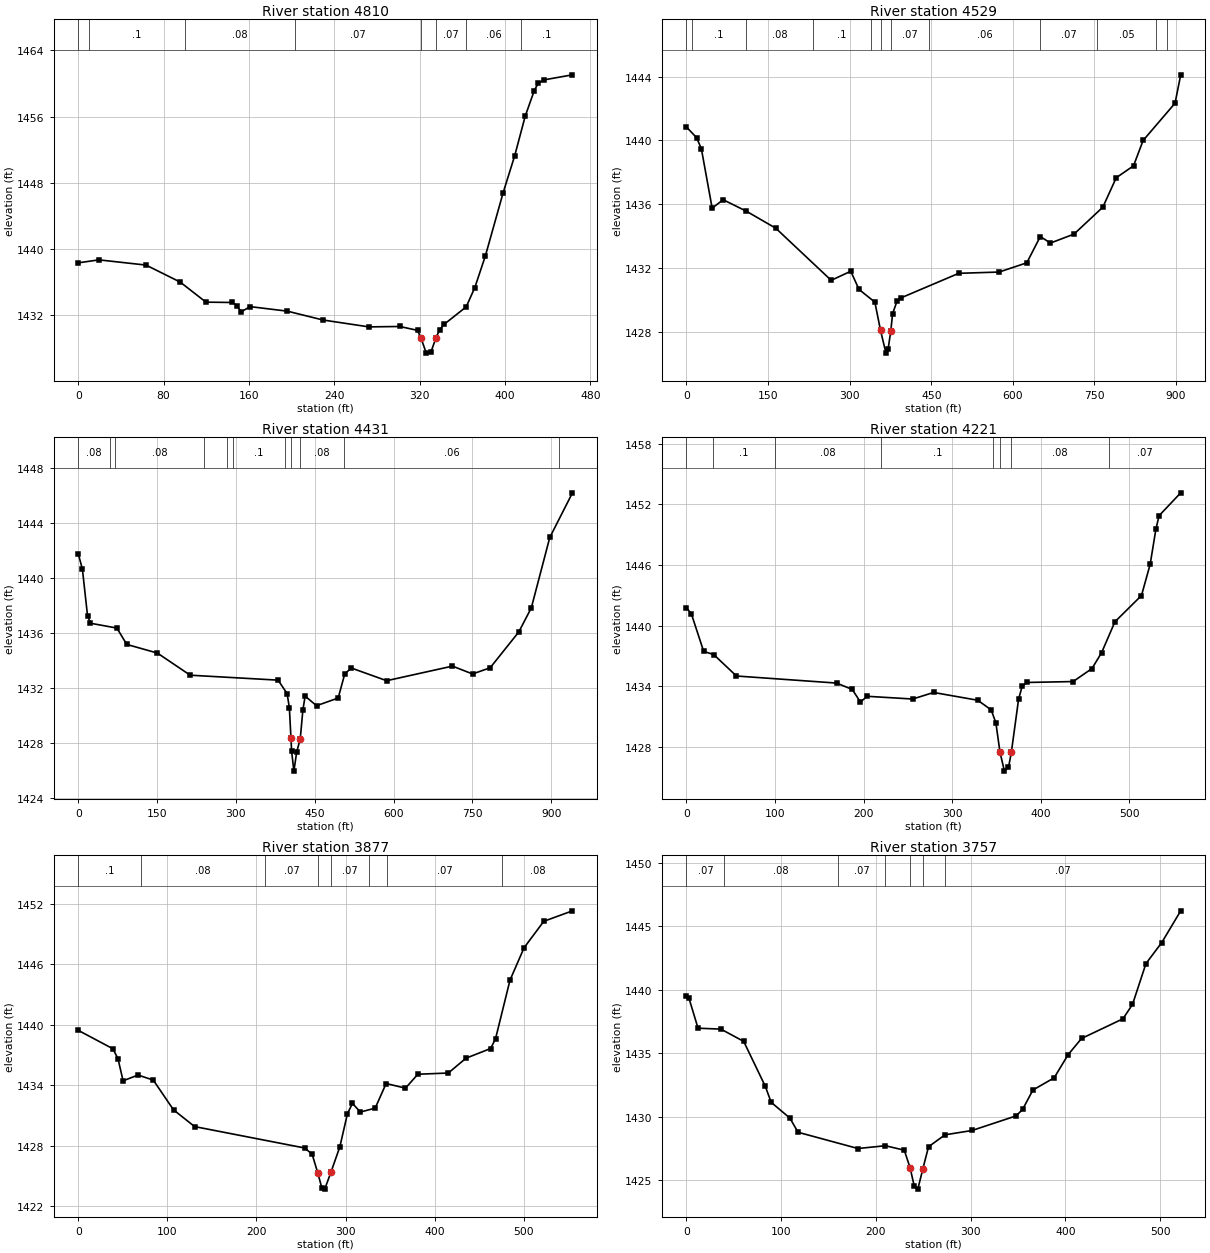
Type RM Length L Ch R = 1 ,4810    ,278.2,281.1,278.6
XS GIS Cut Line= 4
2183465.34268093715808.6180337342183462.87376646715695.047968435
 2183397.4475332715441.9842359782183336.95912885715377.792459939
#Sta/Elev= 30
       0 1438.33    19.4 1438.69    63.5 1438.06    95.5 1436.01   119.7 1433.58
   144.4 1433.54   148.6 1433.17   152.7  1432.4     161 1433.04     196 1432.49
   229.5 1431.42   272.5 1430.59   301.4 1430.64     318 1430.17   321.31429.211
   326.2 1427.42   330.4  1427.5   335.31429.276   338.6 1430.21   342.8 1430.89
   363.6 1433.01   371.7 1435.35   381.6 1439.18   398.1 1446.75   409.1 1451.29
   418.9 1456.05   427.4 1459.15     431 1460.01   436.5 1460.44   463.2 1461.05
#Mann= 8 ,-1,0
       0     .08       0      10      .1       0     100     .08       0
   203.6     .07       0   321.3    .045       0   335.3     .07       0
   363.6     .06       0  414.98      .1       0
Bank Sta=321.3,335.3
XS Rating Curve= 0 ,0
Exp/Cntr(USF)=0,0
Exp/Cntr=0.3,0.1

Type RM Length L Ch R = 1 ,4529    ,98.6,98.1,95.3
XS GIS Cut Line= 6
 2183595.5048731 715890.684763432183722.13729617715721.306862407
2183663.41344345 715608.237289962183653.02741804715551.722977615
 2183540.1536111715255.3486358042183494.91177952715065.907525008
#Sta/Elev= 30
       0 1440.84    18.7 1440.17    27.4 1439.47    47.2 1435.75    67.4 1436.28
     110 1435.56   164.2 1434.49     266 1431.22     302 1431.79   317.1 1430.65
   346.3 1429.85  356.67 1428.08   366.7 1426.65   370.7 1426.92   375.5 1428.02
   378.9 1429.13     387 1429.91   393.7 1430.11   500.5 1431.66   574.8 1431.74
   625.6 1432.32   650.4 1433.97     669 1433.56   712.3 1434.12   765.3 1435.81
     790 1437.66   821.8 1438.41   839.4    1440   898.1 1442.34   908.5 1444.12
#Mann= 12 ,-1,0
       0     .08       0      10      .1       0     110     .08       0
  231.74      .1       0  339.15     .07       0  356.67    .045       0
   375.5     .07       0  446.61     .06       0  650.44     .07       0
  753.75     .05       0  863.75     .08       0  883.75     .05       0
Bank Sta=356.67,375.5
XS Rating Curve= 0 ,0
Exp/Cntr(USF)=0,0
Exp/Cntr=0.3,0.1

Type RM Length L Ch R = 1 ,4431    ,198.3,210,225.5
XS GIS Cut Line= 4
2183662.18796325715947.6512091542183807.12967656715739.305248842
2183742.14253442715569.5046132962183591.45492562715087.706564502
#Sta/Elev= 30
       0 1441.74     7.9 1440.63    17.6 1437.25    23.3 1436.69    73.5 1436.34
    92.3 1435.15   150.6 1434.52     213 1432.91   380.3 1432.55   397.4 1431.57
   401.7 1430.55  404.731428.339     406 1427.37   410.3 1425.93   415.7 1427.33
422.4155 1428.28   427.4 1430.37   431.7 1431.39   453.4 1430.69   494.6 1431.25
   507.2 1433.02   519.8 1433.43   586.8 1432.51     712 1433.57   750.3    1433
   783.8 1433.45   838.3 1436.06   862.1 1437.81   897.2 1442.93   940.4 1446.18
#Mann= 11 ,-1,0
       0     .08       0      60      .1       0      70     .08       0
     240      .1       0   283.8     .08       0   293.8      .1       0
   393.8     .08       0  404.73    .045       0422.4155     .08       0
  505.62     .06       0  915.62     .08       0
Bank Sta=404.73,422.4155
XS Rating Curve= 0 ,0
Exp/Cntr(USF)=0,0
Exp/Cntr=0.3,0.1

Type RM Length L Ch R = 1 ,4221    ,340.1,343.4,344.2
XS GIS Cut Line= 3
2183680.74451747715977.0213181092183892.32975105715715.174268928
2184024.87552929715537.634498183
#Sta/Elev= 30
       0 1441.75     5.5 1441.16    19.4 1437.44    30.8 1437.12    56.4    1435
   169.5  1434.3   187.2 1433.67   196.4 1432.43   204.3 1432.99   255.5 1432.72
   279.1 1433.37   328.9  1432.6   344.1 1431.65   349.4 1430.38   354.1 1427.45
   359.1 1425.58   363.7 1425.95   366.9 1427.43   375.1 1432.71   379.1 1433.97
   384.1 1434.36   436.7 1434.45     458 1435.74   468.9 1437.32   483.9 1440.37
   513.9 1442.97   523.7 1446.06   530.3  1449.6   533.8 1450.88   558.2 1453.14
#Mann= 8 ,-1,0
       0     .08       0      30      .1       0     100     .08       0
     220      .1       0  346.65     .08       0   354.1    .045       0
   366.9     .08       0  476.65     .07       0
Bank Sta=354.1,366.9
XS Rating Curve= 0 ,0
Exp/Cntr=0.3,0.1

Type RM Length L Ch R = 1 ,3877    ,121.9,120.2,118.4
XS GIS Cut Line= 3
2183944.10113286716128.2069565422184134.75413742715942.772107716
2184347.93568054715748.198218401
#Sta/Elev= 30
       0 1439.46    38.8 1437.64    44.6 1436.65    50.3 1434.46    67.1 1435.03
    84.2 1434.53   106.9 1431.58   130.6 1429.92   253.9  1427.8   262.4  1427.2
   268.8 1425.32   273.3 1423.85   276.6 1423.72  283.491425.379   293.6 1427.93
   302.1 1431.21   307.7 1432.22   316.6 1431.36   333.2 1431.75   345.5 1434.19
   367.2 1433.73   381.1 1435.11   415.3 1435.23   435.1  1436.7   462.8 1437.66
   468.3 1438.64   484.5 1444.44   500.3 1447.65   522.4 1450.27   554.6 1451.31
#Mann= 8 ,-1,0
       0      .1       0      70     .08       0     210     .07       0
   268.8    .045       0  283.49     .07       0  325.96     .08       0
  345.96     .07       0  475.96     .08       0
Bank Sta=268.8,283.49
XS Rating Curve= 0 ,0
Exp/Cntr=0.3,0.1

Type RM Length L Ch R = 1 ,3757    ,30.4,30.4,30.4
XS GIS Cut Line= 4
2184074.77146024716227.2624202282184192.21093173716053.128031467
2184231.08744643716003.7224607022184414.94096387715836.067491057
#Sta/Elev= 30
       0 1439.55     2.5 1439.37    12.2 1436.98    36.3 1436.91    60.4 1435.94
    83.2  1432.4    89.4 1431.14   109.1  1429.9   117.8 1428.78     181  1427.5
     210 1427.72   229.9 1427.37   236.11425.964   240.5 1424.51   244.2  1424.3
   249.51425.897   255.5 1427.64   272.9 1428.58   301.4 1428.92   347.9 1430.07
   354.8 1430.58   365.7 1432.11   388.1 1433.07   402.9  1434.9     417 1436.17
   460.7 1437.72   470.8 1438.85     485 1442.07   501.7 1443.73   521.7 1446.23
#Mann= 7 ,-1,0
       0     .07       0      40     .08       0     160     .07       0
     210     .08       0   236.1    .045       0   249.5     .08       0
   272.9     .07       0
Bank Sta=236.1,249.5
XS Rating Curve= 0 ,0
Exp/Cntr(USF)=0,0
Exp/Cntr=0.3,0.1

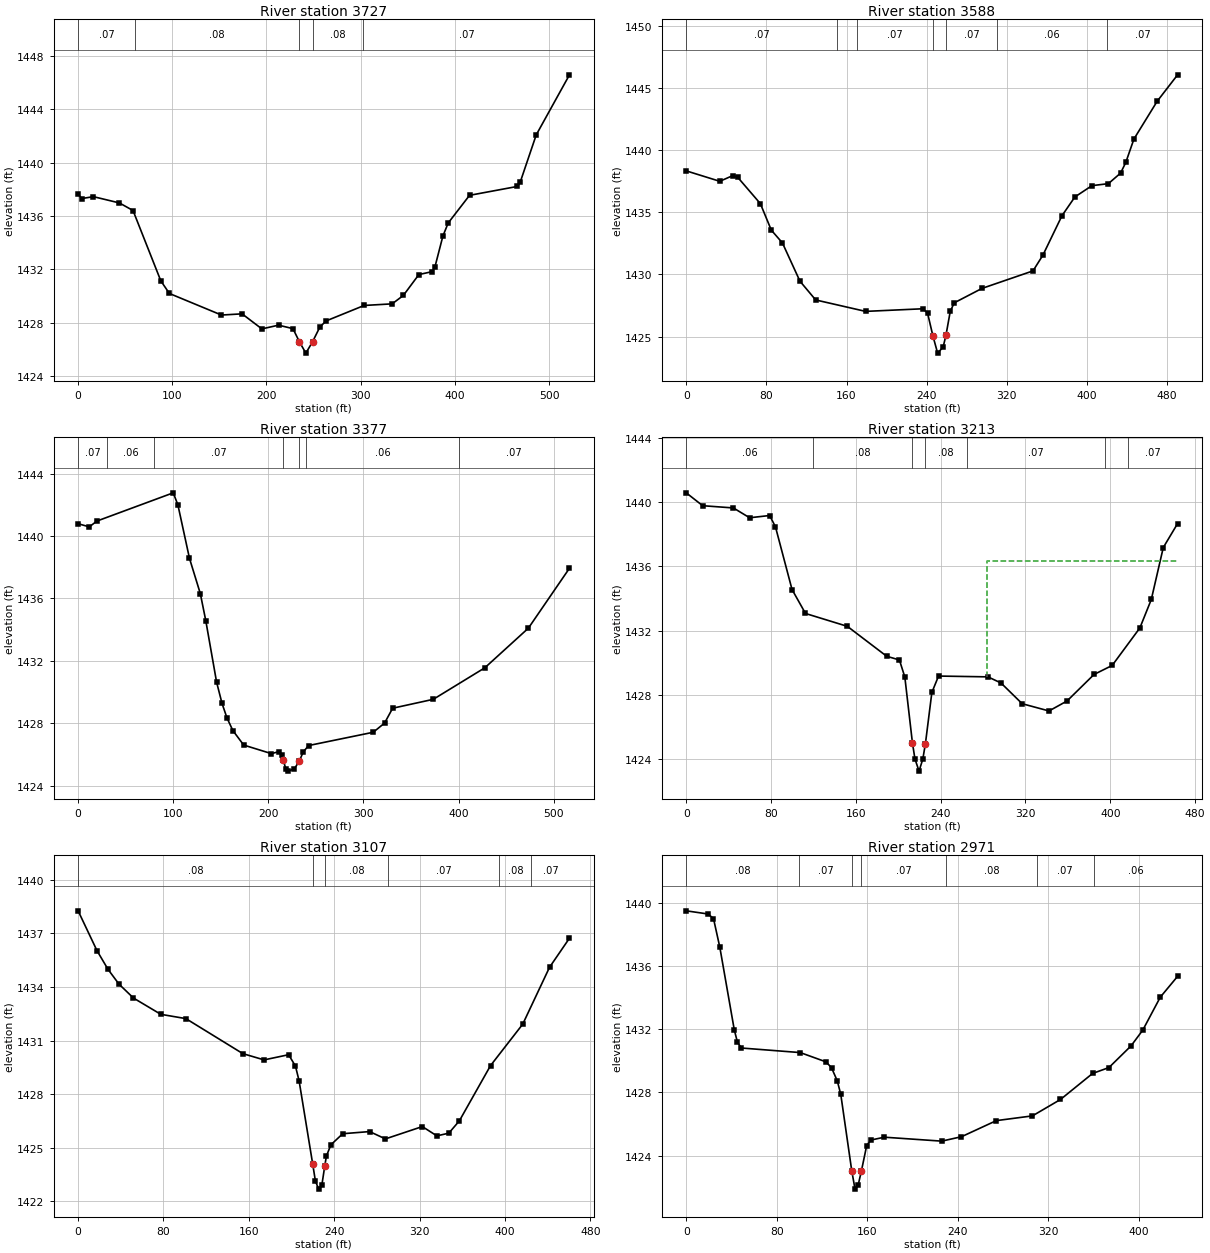
Type RM Length L Ch R = 1 ,3727    ,136.8,138.3,138.9
XS GIS Cut Line= 4
2184099.06928193716245.4857864942184216.50875342716071.351397732
2184255.38526812716021.9458269672184439.23878556715854.290857322
#Sta/Elev= 30
       0 1437.64     3.9 1437.31    16.3 1437.45    43.8 1436.98    58.3 1436.41
    87.8 1431.13    96.9 1430.18   152.2 1428.56   174.1 1428.65   195.1 1427.52
   212.8  1427.8   228.1 1427.54     2351426.546   241.8  1425.7   248.9 1426.55
   256.9 1427.69   263.7 1428.13   303.7 1429.28   333.4  1429.4   345.3 1430.03
   361.8  1431.6   375.9 1431.82   378.8 1432.16   387.3 1434.49   392.9 1435.47
   415.6 1437.55   466.5 1438.22   469.4 1438.54   486.4 1442.09   521.7  1446.6
#Mann= 5 ,-1,0
       0     .07       0      60     .08       0     235    .045       0
   248.9     .08       0   302.9     .07       0
Bank Sta=235,248.9
XS Rating Curve= 0 ,0
Exp/Cntr(USF)=0,0
Exp/Cntr=0.3,0.1

Type RM Length L Ch R = 1 ,3588    ,210.9,211.5,213.3
XS GIS Cut Line= 2
2184177.05351404716302.5501806462184515.90781172715948.056206257
#Sta/Elev= 30
       0 1438.34    33.5  1437.5    46.2 1437.95    51.3 1437.83      74  1435.7
    84.9 1433.57      96 1432.54   113.5 1429.46   129.2 1427.95     179 1427.03
   236.1 1427.24   240.8 1426.91  246.191425.058   250.9 1423.67   256.4 1424.16
   259.2  1425.1   263.5 1427.03   267.5 1427.72   295.2 1428.88   346.1 1430.29
     356 1431.56     375 1434.73   387.9 1436.24   404.9 1437.15   421.3 1437.31
   433.5 1438.16   438.7 1439.02   446.8  1440.9     470 1443.94   490.4 1446.07
#Mann= 7 ,-1,0
       0     .07       0     150     .08       0     170     .07       0
  246.19    .045       0   259.2     .07       0     310     .06       0
     420     .07       0
Bank Sta=246.19,259.2
XS Rating Curve= 0 ,0
Exp/Cntr(USF)=0,0
Exp/Cntr=0.3,0.1

Type RM Length L Ch R = 1 ,3377    ,164.4,164.2,163.4
XS GIS Cut Line= 2
2184272.68984317716442.221618309 2184678.0170265716122.001083827
#Sta/Elev= 30
       0 1440.79    11.8 1440.59    19.7 1440.96     100 1442.77   104.9    1442
   117.1 1438.57   128.5 1436.31   134.2 1434.59   145.6 1430.64   151.3 1429.28
   156.5 1428.35   162.7 1427.54   174.1 1426.61   203.3 1426.06   211.1 1426.19
     214    1426  215.751425.644   218.5 1425.05   221.1 1424.94   227.5  1425.1
  232.641425.596   236.7 1426.17   242.4 1426.58   310.3 1427.43   322.2 1428.02
   330.7 1428.97   373.4 1429.54   427.6 1431.56   473.4  1434.1   516.6 1437.94
#Mann= 7 ,-1,0
       0     .07       0      30     .06       0      80     .07       0
  215.75    .045       0  232.64     .07       0     240     .06       0
     400     .07       0
Bank Sta=215.75,232.64
XS Rating Curve= 0 ,0
Exp/Cntr(USF)=0,0
Exp/Cntr=0.3,0.1

Type RM Length L Ch R = 1 ,3213    ,106,106.2,106.6
XS GIS Cut Line= 4
2184388.42096194716568.1137545152184574.30186067716408.707845292
2184696.25564668716301.626472203 2184739.5657118716265.565751957
#Sta/Elev= 30
       0 1440.57    15.5 1439.77    44.5 1439.63    59.8 1439.02    78.7 1439.16
    84.2 1438.45    99.8 1434.56   112.5 1433.07     152 1432.27   189.1 1430.41
   201.1 1430.18   206.2 1429.12  213.341425.045   215.7 1424.04   219.6 1423.27
   223.2 1424.03  225.641424.986   231.7 1428.16     238 1429.18   284.6 1429.13
   296.9 1428.75   316.9 1427.46   342.2 1427.01   359.2 1427.63   384.7 1429.28
   401.8 1429.84   427.9 1432.17   438.7 1433.94     450 1437.17   463.5 1438.66
#Mann= 7 ,-1,0
       0     .06       0     120     .08       0  213.34    .045       0
  225.64     .08       0  264.87     .07       0  394.87     .08       0
  417.16     .07       0
#XS Ineff= 2 , 0
                          283.25         1436.31
Permanent Ineff=
       F       F
Bank Sta=213.34,225.64
XS Rating Curve= 0 ,0
Exp/Cntr(USF)=0,0
Exp/Cntr=0.3,0.1

Type RM Length L Ch R = 1 ,3107    ,135.1,135.1,134.5
XS GIS Cut Line= 4
2184458.23228157716636.1449778412184662.03209602716473.718718799
2184754.32981697716406.4394030192184806.28826337716338.318881067
#Sta/Elev= 30
       0 1438.26    17.7 1436.03    28.1 1434.98    38.3 1434.16    51.9 1433.38
    77.5 1432.47     101 1432.23   154.4 1430.27   174.3 1429.92   197.3 1430.21
   203.7 1429.57   207.1 1428.75  219.881424.083   222.4 1423.14   225.5 1422.69
   228.4  1422.9   231.2    1424   232.7 1424.54   236.9 1425.17     248 1425.79
   273.2 1425.91     288  1425.5   322.6 1426.19   336.2 1425.67   347.4 1425.82
   357.3 1426.51   386.5  1429.6   416.7 1431.92   441.8  1435.1   460.5 1436.73
#Mann= 6 ,-1,0
       0     .08       0  219.88    .045       0   231.2     .08       0
  290.61     .07       0  394.82     .08       0  424.82     .07       0
Bank Sta=219.88,231.2
XS Rating Curve= 0 ,0
Exp/Cntr(USF)=0,0
Exp/Cntr=0.3,0.1

Type RM Length L Ch R = 1 ,2971    ,163.5,165.6,167.2
XS GIS Cut Line= 2
 2184605.2710319 716692.248963372184939.89864454716415.447160285
#Sta/Elev= 30
       0  1439.5    19.3  1439.3    24.1 1439.01    29.7 1437.19    42.5 1431.95
    45.3 1431.17    48.7 1430.81   100.8 1430.52   123.6 1429.93   128.4 1429.56
   133.5 1428.73   136.6 1427.87   146.3 1423.03   149.2 1421.87     152 1422.14
   154.8 1423.01   159.5 1424.63   163.3 1424.98   175.1 1425.16   225.8 1424.91
   243.3 1425.19   274.1 1426.21     306 1426.51   330.8 1427.55   359.2  1429.2
   373.6 1429.57   393.1 1430.94   403.5 1431.94     419 1434.03   434.3 1435.35
#Mann= 7 ,-1,0
       0     .08       0     100     .07       0   146.3    .045       0
   154.8     .07       0     230     .08       0     310     .07       0
     360     .06       0
Bank Sta=146.3,154.8
XS Rating Curve= 0 ,0
Exp/Cntr(USF)=0,0
Exp/Cntr=0.3,0.1

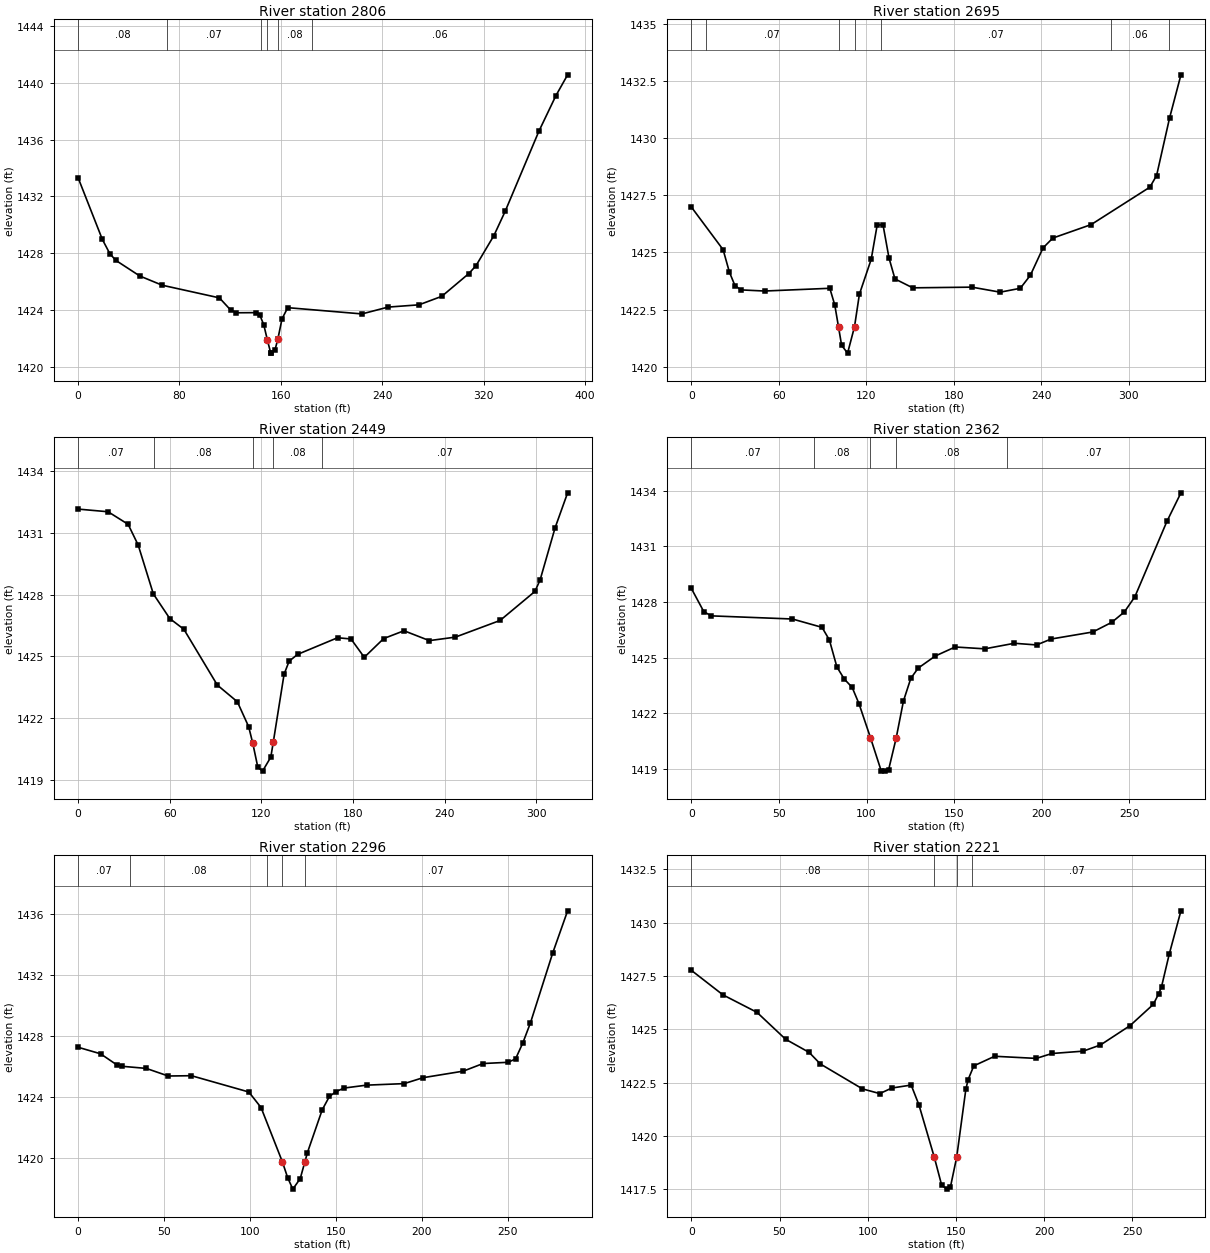
Type RM Length L Ch R = 1 ,2806    ,104,110.4,116.8
XS GIS Cut Line= 3
2184722.04602607716757.1538870952184796.14492194716716.699242943
2185064.34233953716578.595414829
#Sta/Elev= 30
       0 1433.33    19.2 1428.97    25.1 1427.97    29.8  1427.5    48.7  1426.4
    66.4 1425.75   111.5 1424.86   120.4    1424   124.9 1423.81   140.5 1423.82
   143.5 1423.62   146.5 1422.96   149.4 1421.87   151.9    1421   152.4 1420.97
   155.4 1421.22  157.531421.937   160.9 1423.39   165.4 1424.17   223.9 1423.73
   244.5 1424.21   268.9 1424.37   286.9 1424.97   308.2 1426.57   313.9 1427.13
     328 1429.25   336.8 1430.94   363.4 1436.58   376.9  1439.1   386.1 1440.56
#Mann= 6 ,-1,0
       0     .08       0      70     .07       0  144.42     .08       0
   149.4    .045       0  157.53     .08       0  184.42     .06       0
Bank Sta=149.4,157.53
XS Rating Curve= 0 ,0
Exp/Cntr(USF)=0,0
Exp/Cntr=0.3,0.1

Type RM Length L Ch R = 1 ,2695    ,259.3,246.9,230.2
XS GIS Cut Line= 4
 2184774.7389735716768.2928272252184903.94603599716791.716329781
2185018.71441476716812.5288968852185089.64920624716760.598919471
#Sta/Elev= 30
       0 1426.99    21.8 1425.12    26.1 1424.14    29.9 1423.55      34 1423.36
    50.2 1423.31      95 1423.43    98.4  1422.7     1011421.724   103.1 1420.93
   107.2 1420.59  111.941421.746   115.3 1423.17   123.4  1424.7   127.5  1426.2
   131.5 1426.21   135.6 1424.76   139.7 1423.84   151.9 1423.45   192.5 1423.48
   211.9 1423.26   225.7 1423.43   232.6    1424   241.3  1425.2     248 1425.63
   274.3 1426.22   314.6 1427.86   319.2 1428.37   328.1 1430.89   335.9 1432.78
#Mann= 7 ,-1,0
       0     .08       0      10     .07       0     101    .045       0
  111.94     .06       0     130     .07       0  287.95     .06       0
  327.95     .07       0
Bank Sta=101,111.94
XS Rating Curve= 0 ,0
Exp/Cntr(USF)=0,0
Exp/Cntr=0.3,0.1

Type RM Length L Ch R = 1 ,2449    ,87.5,86.8,85.4
XS GIS Cut Line= 3
2184920.22067787717028.5459051892184995.78036353716857.836985728
2185097.87828866716771.340269395
#Sta/Elev= 30
       0 1432.16    19.7 1432.03    32.8 1431.42    39.4 1430.41    49.3 1428.04
    60.1 1426.84    69.3 1426.32    91.2 1423.61   104.3  1422.8   111.7 1421.59
   114.41420.782   117.7 1419.62   120.8 1419.43   126.2 1420.11   127.81420.826
   134.9 1424.14   138.2 1424.77   143.7  1425.1   169.9 1425.91   178.7 1425.85
   187.4 1424.96   200.1 1425.87   213.4 1426.25     230 1425.77     247 1425.94
   276.3 1426.75   299.1 1428.16   302.5 1428.72   312.3 1431.25   320.5 1432.95
#Mann= 5 ,-1,0
       0     .07       0      50     .08       0   114.4    .045       0
   127.8     .08       0     160     .07       0
Bank Sta=114.4,127.8
XS Rating Curve= 0 ,0
Exp/Cntr(USF)=0,0
Exp/Cntr=0.3,0.1

Type RM Length L Ch R = 1 ,2362    ,65.7,66,66.4
XS GIS Cut Line= 3
2185014.43707604717051.8667958252185083.66249213 716847.29907972
2185125.42298573716799.469117817
#Sta/Elev= 30
       0 1428.73     7.1 1427.48    11.3 1427.25    57.7 1427.08    74.6 1426.63
    78.8 1425.95    83.1 1424.49    87.3 1423.84    91.8 1423.39    95.7 1422.51
  102.251420.677   108.4 1418.88   110.8 1418.87   112.6 1418.94   116.9 1420.64
   121.1 1422.66   125.3 1423.88   129.5 1424.43   139.2 1425.08   150.6 1425.57
   167.5 1425.47   184.4 1425.77   197.1 1425.68   205.4    1426   229.2 1426.38
     240  1426.9   247.2 1427.46   253.2 1428.28   271.5 1432.35   279.5 1433.89
#Mann= 5 ,-1,0
       0     .07       0      70     .08       0  102.25    .045       0
   116.9     .08       0     180     .07       0
Bank Sta=102.25,116.9
XS Rating Curve= 0 ,0
Exp/Cntr(USF)=0,0
Exp/Cntr=0.3,0.1

Type RM Length L Ch R = 1 ,2296    ,73.8,75,75.9
XS GIS Cut Line= 3
2185068.54154232717086.3817139682185120.78033735716945.523534522
2185172.45477862716821.201131642
#Sta/Elev= 30
       0 1427.27    13.1 1426.84    22.6 1426.11    25.5 1426.02    39.7 1425.88
    52.5 1425.38      66  1425.4    99.4 1424.33   106.5 1423.31   118.9 1419.75
     122  1418.7     125 1417.95   129.3 1418.64  132.05 1419.76   133.5 1420.35
   142.1 1423.16   146.3 1424.04   150.2 1424.36   154.9 1424.59   167.9 1424.78
   189.8 1424.88   200.8 1425.27   224.2  1425.7   235.7  1426.2   250.2 1426.28
   254.6  1426.5   258.9 1427.57   263.3 1428.88   276.2 1433.45   284.9 1436.23
#Mann= 5 ,-1,0
       0     .07       0      30     .08       0     110     .07       0
   118.9    .045       0  132.05     .07       0
Bank Sta=118.9,132.05
XS Rating Curve= 0 ,0
Exp/Cntr(USF)=0,0
Exp/Cntr=0.3,0.1

Type RM Length L Ch R = 1 ,2221    ,114.8,114.9,114.6
XS GIS Cut Line= 3
2185118.60372089717125.2498650292185179.23803654717000.249891216
2185238.93951657716875.249917403
#Sta/Elev= 30
       0 1427.77    17.9 1426.62    37.2  1425.8    53.4 1424.54    66.8 1423.92
    73.1 1423.38      97 1422.21   106.8 1421.99   113.6 1422.25   124.6 1422.39
     129 1421.46  137.711419.005   141.9 1417.69   144.9 1417.51   146.8 1417.59
   150.4 1419.01   155.6  1422.2   156.9 1422.65   160.1 1423.29   171.9 1423.74
   195.5 1423.64   204.4 1423.87   222.1 1423.98   231.9 1424.27   248.7 1425.18
   261.8 1426.17   264.9 1426.67   266.5    1427   270.9 1428.54   277.5 1430.56
#Mann= 4 ,-1,0
       0     .08       0  137.71    .045       0   150.4     .08       0
  158.93     .07       0
Bank Sta=137.71,150.4
XS Rating Curve= 0 ,0
Exp/Cntr(USF)=0,0
Exp/Cntr=0.3,0.1

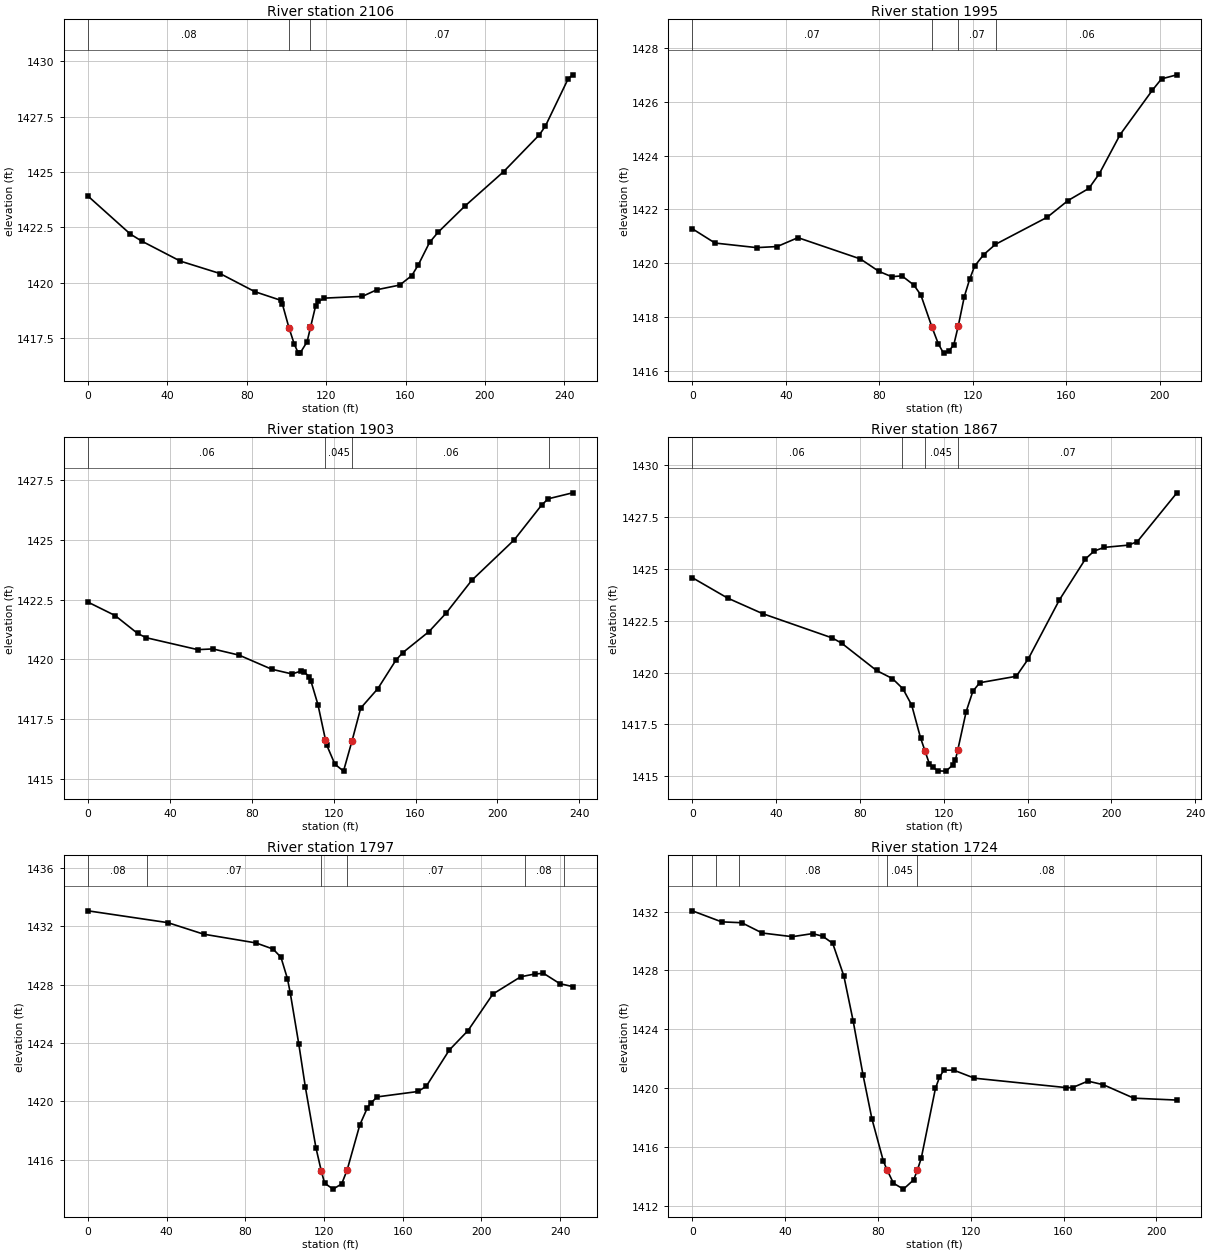
Type RM Length L Ch R = 1 ,2106    ,109.4,110.9,110.1
XS GIS Cut Line= 3
2185231.47683157717157.8991119212185283.71562659717041.294658737
2185333.15591474716935.884233059
#Sta/Elev= 30
       0 1423.91    21.3  1422.2    27.1 1421.88    46.5 1420.98    66.5 1420.42
    84.1  1419.6    97.2 1419.21    97.9 1419.06  101.24 1417.98     104 1417.22
     106 1416.83     107 1416.85   110.4 1417.34   112.11417.986   114.7 1418.96
   116.1 1419.16   119.1 1419.31   138.3 1419.39   145.6 1419.69   157.1  1419.9
   163.2 1420.33   166.5 1420.82   172.1 1421.82   176.3 1422.27   189.8 1423.45
   209.4 1425.01   227.5 1426.68   230.5 1427.07   241.9 1429.19   244.2 1429.38
#Mann= 3 ,-1,0
       0     .08       0  101.24    .045       0   112.1     .07       0
Bank Sta=101.24,112.1
XS Rating Curve= 0 ,0
Exp/Cntr(USF)=0,0
Exp/Cntr=0.3,0.1

Type RM Length L Ch R = 1 ,1995    ,93.1,91.6,89.6
XS GIS Cut Line= 2
2185318.23054474717185.8841806852185408.71560041716999.317055591
#Sta/Elev= 30
       0 1421.28     9.7 1420.75    27.5 1420.58    36.3 1420.62    45.2 1420.95
    71.9 1420.16    79.8  1419.7    85.3  1419.5    89.7 1419.53    94.8 1419.19
    97.8 1418.82   102.61417.615   105.3    1417   107.5 1416.66   109.8 1416.74
   111.9 1416.97   113.81417.666   116.4 1418.76   118.7 1419.41   120.8 1419.89
   124.7 1420.32   129.7  1420.7   151.9 1421.71   160.8 1422.33   169.7 1422.78
   174.2 1423.33   183.1 1424.78   196.9 1426.43   200.8 1426.85   207.4    1427
#Mann= 4 ,-1,0
       0     .07       0   102.6    .045       0   113.8     .07       0
     130     .06       0
Bank Sta=102.6,113.8
XS Rating Curve= 0 ,0
Exp/Cntr(USF)=0,0
Exp/Cntr=0.3,0.1

Type RM Length L Ch R = 1 ,1903    ,36.5,36.4,36
XS GIS Cut Line= 3
2185406.79395902717252.2927488622185450.31633796717113.565165985
2185475.47771329 717025.84037093
#Sta/Elev= 30
       0 1422.39    13.2 1421.83    24.2 1421.08    28.4  1420.9    53.6  1420.4
      61 1420.43    73.8 1420.17    89.7 1419.58    99.7 1419.38   103.9  1419.5
   105.7 1419.45   108.1 1419.27   108.9 1419.08   112.3  1418.1  115.971416.628
   116.5 1416.42   120.6  1415.6   124.8 1415.31     129 1416.59   133.2 1417.95
   141.6 1418.77   150.4 1419.96   153.7 1420.27   166.6 1421.16   174.9 1421.93
   187.4  1423.3   208.2    1425   221.6 1426.46   224.8 1426.72   236.7 1426.97
#Mann= 4 ,-1,0
       0     .06       0  115.97    .045       0     129     .06       0
  225.39     .07       0
Bank Sta=115.97,129
XS Rating Curve= 0 ,0
Exp/Cntr(USF)=0,0
Exp/Cntr=0.3,0.1

Type RM Length L Ch R = 1 ,1867    ,68.3,69.6,71.5
XS GIS Cut Line= 3
2185440.79581757 717265.213455112185480.23797348717137.366466968
2185504.03927447717042.841300204
#Sta/Elev= 30
       0 1424.57    16.8 1423.59    33.5 1422.84    66.7 1421.67    71.2 1421.42
    87.9  1420.1    95.5 1419.71   100.5 1419.22   104.7 1418.43   108.9 1416.86
   111.11416.205   113.1 1415.61   114.7 1415.45   117.2 1415.26   121.1 1415.25
   124.3 1415.55   125.6 1415.81  126.67 1416.26   130.7 1418.12   133.9  1419.1
   137.2 1419.51   154.6 1419.82   160.3 1420.65   175.2  1423.5   187.6 1425.47
   191.7 1425.85   196.5 1426.03   208.2 1426.14   212.4 1426.31   231.3 1428.66
#Mann= 4 ,-1,0
       0     .06       0     100     .07       0   111.1    .045       0
  126.67     .07       0
Bank Sta=111.1,126.67
XS Rating Curve= 0 ,0
Exp/Cntr(USF)=0,0
Exp/Cntr=0.3,0.1

Type RM Length L Ch R = 1 ,1797    ,73.1,73.1,73.1
XS GIS Cut Line= 3
2185485.12789783717303.5091560432185545.65120605717164.101535994
2185576.93291591717075.016666598
#Sta/Elev= 30
       0 1433.05    40.6 1432.24    58.8 1431.45    85.4 1430.85    94.1 1430.43
    98.1 1429.87   101.4  1428.4   102.8 1427.45   107.2  1423.9   110.5 1420.98
   115.9 1416.81   118.6 1415.23   120.3 1414.39   124.6 1413.98     129 1414.34
   131.8 1415.31   138.2 1418.38   142.1 1419.57     144  1419.9     147  1420.3
   167.8 1420.67     172 1421.03   183.7 1423.51   193.2 1424.84   205.9 1427.35
     220 1428.53   227.1 1428.72   231.6 1428.77   239.9 1428.06   246.4 1427.86
#Mann= 6 ,-1,0
       0     .08       0      30     .07       0   118.6    .045       0
   131.8     .07       0  221.98     .08       0  241.98     .07       0
Bank Sta=118.6,131.8
XS Rating Curve= 0 ,0
Exp/Cntr(USF)=0,0
Exp/Cntr=0.3,0.1

Type RM Length L Ch R = 1 ,1724    ,44.4,45.2,46.5
XS GIS Cut Line= 4
2185566.05232118717300.7890073592185610.25473729717198.103394543
2185622.95664432717170.7623694162185663.38041935717117.386057555
#Sta/Elev= 30
       0 1432.06    12.6 1431.31    21.3 1431.25    30.1 1430.55    43.1  1430.3
    51.8 1430.51    56.2 1430.33    60.5 1429.85    65.3 1427.63    69.3 1424.58
    73.6 1420.87    77.4 1417.91    82.3 1415.05    83.91414.439    86.7 1413.52
      91 1413.12    95.4 1413.75      971414.412    98.7 1415.24   104.8 1419.98
   106.5 1420.72   108.4 1421.22   112.8 1421.21   121.6 1420.67   161.1 1420.03
   163.9 1420.03   170.5 1420.47   177.1 1420.23   190.3 1419.31   208.9 1419.18
#Mann= 5 ,-1,0
       0     .08       0      10      .1       0      20     .08       0
    83.9    .045       0      97     .08       0
Bank Sta=83.9,97
XS Rating Curve= 0 ,0
Exp/Cntr(USF)=0,0
Exp/Cntr=0.3,0.1

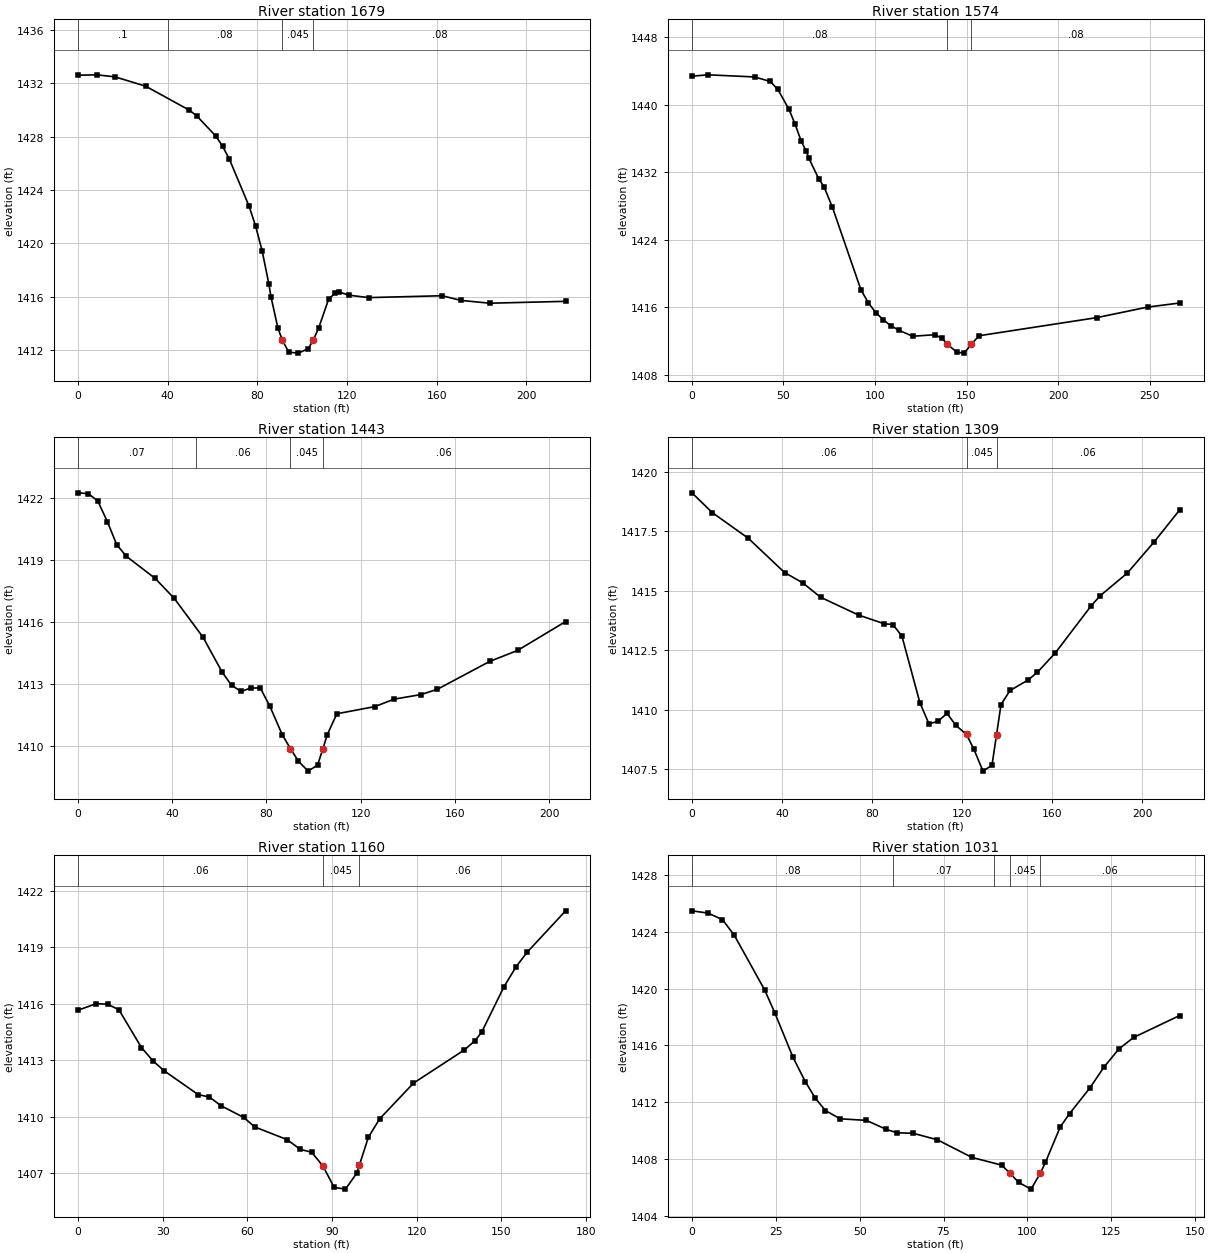
Type RM Length L Ch R = 1 ,1679    ,109,105.2,100.1
XS GIS Cut Line= 4
2185599.37414255 717315.749825122185647.65678169717225.984918552
2185675.60236905  717171.11101662185709.29155699717128.863906735
#Sta/Elev= 30
       0  1432.6     8.4 1432.63    16.5 1432.48    30.2 1431.78    49.7 1429.98
    52.9 1429.57    61.6 1428.02    64.5 1427.28    67.5 1426.33    76.3  1422.8
    79.3 1421.27    82.2  1419.4    85.2 1416.93    86.1    1416    89.2 1413.65
    91.1 1412.78      94 1411.85    98.3 1411.78   102.8 1412.12104.98991412.784
   107.3 1413.63   111.8 1415.82   114.8 1416.29   116.3 1416.37   120.8 1416.12
   129.8 1415.94   162.4 1416.08   170.8 1415.73   183.7 1415.52   217.5 1415.66
#Mann= 4 ,-1,0
       0      .1       0      40     .08       0    91.1    .045       0
104.9899     .08       0
Bank Sta=91.1,104.9899
XS Rating Curve= 0 ,0
Exp/Cntr(USF)=0,0
Exp/Cntr=0.3,0.1

Type RM Length L Ch R = 1 ,1574    ,133.9,130.8,127
XS GIS Cut Line= 3
2185716.93982904717365.4993171662185739.74247766717300.200823383
2185762.54512628717104.305342034
#Sta/Elev= 30
       0 1443.37     8.8 1443.53    34.2 1443.28    42.7 1442.75    46.9 1441.81
      53 1439.44    56.2 1437.76    59.7 1435.66    62.5 1434.45    63.9 1433.62
    69.2 1431.23    72.2 1430.23    76.7 1427.85    92.3 1418.05    96.4  1416.5
   100.4 1415.35   104.4 1414.53   108.5 1413.81   113.1 1413.26   120.5 1412.55
   132.6 1412.73   136.6 1412.32   139.51411.604   144.7 1410.66   148.7 1410.55
   152.61411.597   156.8 1412.61   221.2 1414.76     249 1416.01   266.4 1416.49
#Mann= 3 ,-1,0
       0     .08       0   139.5    .045       0   152.6     .08       0
Bank Sta=139.5,152.6
XS Rating Curve= 0 ,0
Exp/Cntr(USF)=0,0
Exp/Cntr=0.3,0.1

Type RM Length L Ch R = 1 ,1443    ,129.3,133.5,134.5
XS GIS Cut Line= 2
2185887.89232225717325.4817053172185853.13486684717121.470554027
#Sta/Elev= 30
       0 1422.26     4.4 1422.22     8.4 1421.87    12.5 1420.86    16.5 1419.74
    20.6 1419.18    32.8 1418.11    40.9 1417.14    53.1 1415.26    61.2 1413.57
    65.2 1412.93    69.3 1412.63    73.3  1412.8    77.4  1412.8    81.5 1411.91
    86.7 1410.54    90.2 1409.86    93.6 1409.25    97.7 1408.77   101.7 1409.06
     104 1409.86   105.8 1410.53   109.9 1411.55   126.1  1411.9   134.2 1412.26
   145.6 1412.48   152.6 1412.74   174.8 1414.09   186.6 1414.62     207 1416.02
#Mann= 4 ,-1,0
       0     .07       0      50     .06       0    90.2    .045       0
     104     .06       0
Bank Sta=90.2,104
XS Rating Curve= 0 ,0
Exp/Cntr(USF)=0,0
Exp/Cntr=0.3,0.1

Type RM Length L Ch R = 1 ,1309    ,150.7,149.7,147.9
XS GIS Cut Line= 3
2185983.85312304717314.1477524682185989.89789789717227.254113955
2185995.94267275717098.047051471
#Sta/Elev= 30
       0 1419.11       9 1418.28      25  1417.2    41.1 1415.76    49.1 1415.33
    57.1 1414.72      74 1413.97    85.2 1413.61    89.2 1413.57    93.2 1413.09
   101.2 1410.28   105.2  1409.4   109.2  1409.5   113.2 1409.84   117.2 1409.33
   121.9 1408.95   125.2 1408.32   129.2 1407.41   133.2 1407.66   135.21408.935
   137.2 1410.21   141.2  1410.8   149.2 1411.24   153.3 1411.56   161.3 1412.38
   177.3 1414.37   181.3 1414.79   193.3 1415.74   205.3 1417.06   216.5 1418.39
#Mann= 3 ,-1,0
       0     .06       0   121.9    .045       0   135.2     .06       0
Bank Sta=121.9,135.2
XS Rating Curve= 0 ,0
Exp/Cntr(USF)=0,0
Exp/Cntr=0.3,0.1

Type RM Length L Ch R = 1 ,1160    ,132.1,128.5,124.8
XS GIS Cut Line= 2
2186142.06922795717283.6355387112186126.90439904717111.518130739
#Sta/Elev= 30
       0 1415.66     6.5 1416.01    10.5 1415.98    14.5 1415.69    22.5 1413.68
    26.6 1412.97    30.6 1412.44    42.6 1411.18    46.6 1411.05    50.7 1410.59
    58.7 1409.97    62.7 1409.46    74.1 1408.79    78.8 1408.27    82.8 1408.12
    86.8 1407.39    90.8 1406.25    94.8 1406.16    98.8 1407.01   99.741407.441
   102.9 1408.91   106.9 1409.89   118.9 1411.79   136.9 1413.55   140.6 1414.03
     143 1414.48     151 1416.92   155.3 1417.98   159.1 1418.73   172.8 1420.94
#Mann= 3 ,-1,0
       0     .06       0    86.8    .045       0   99.74     .06       0
Bank Sta=86.8,99.74
XS Rating Curve= 0 ,0
Exp/Cntr(USF)=0,0
Exp/Cntr=0.3,0.1

Type RM Length L Ch R = 1 ,1031    ,116.1,122.5,127.4
XS GIS Cut Line= 2
 2186292.4043653717233.5358402512186233.41046068717100.675618085
#Sta/Elev= 30
       0 1425.47     4.8 1425.31     9.1 1424.85    12.6 1423.76    21.7 1419.89
    24.7 1418.29    30.1 1415.17    33.8 1413.44    36.8 1412.27    39.8 1411.41
    44.2 1410.83      52 1410.72      58 1410.08    61.1 1409.85      66 1409.81
    73.2 1409.35    83.5 1408.11    92.3 1407.57   94.721407.025    97.4 1406.35
   101.1 1405.88   103.9 1407.02   105.4 1407.77   109.8 1410.26   112.6  1411.2
   118.6 1412.99   122.9 1414.49   127.3 1415.75   131.7 1416.56   145.4  1418.1
#Mann= 5 ,-1,0
       0     .08       0      60     .07       0      90     .06       0
   94.72    .045       0   103.9     .06       0
Bank Sta=94.72,103.9
XS Rating Curve= 0 ,0
Exp/Cntr(USF)=0,0
Exp/Cntr=0.3,0.1