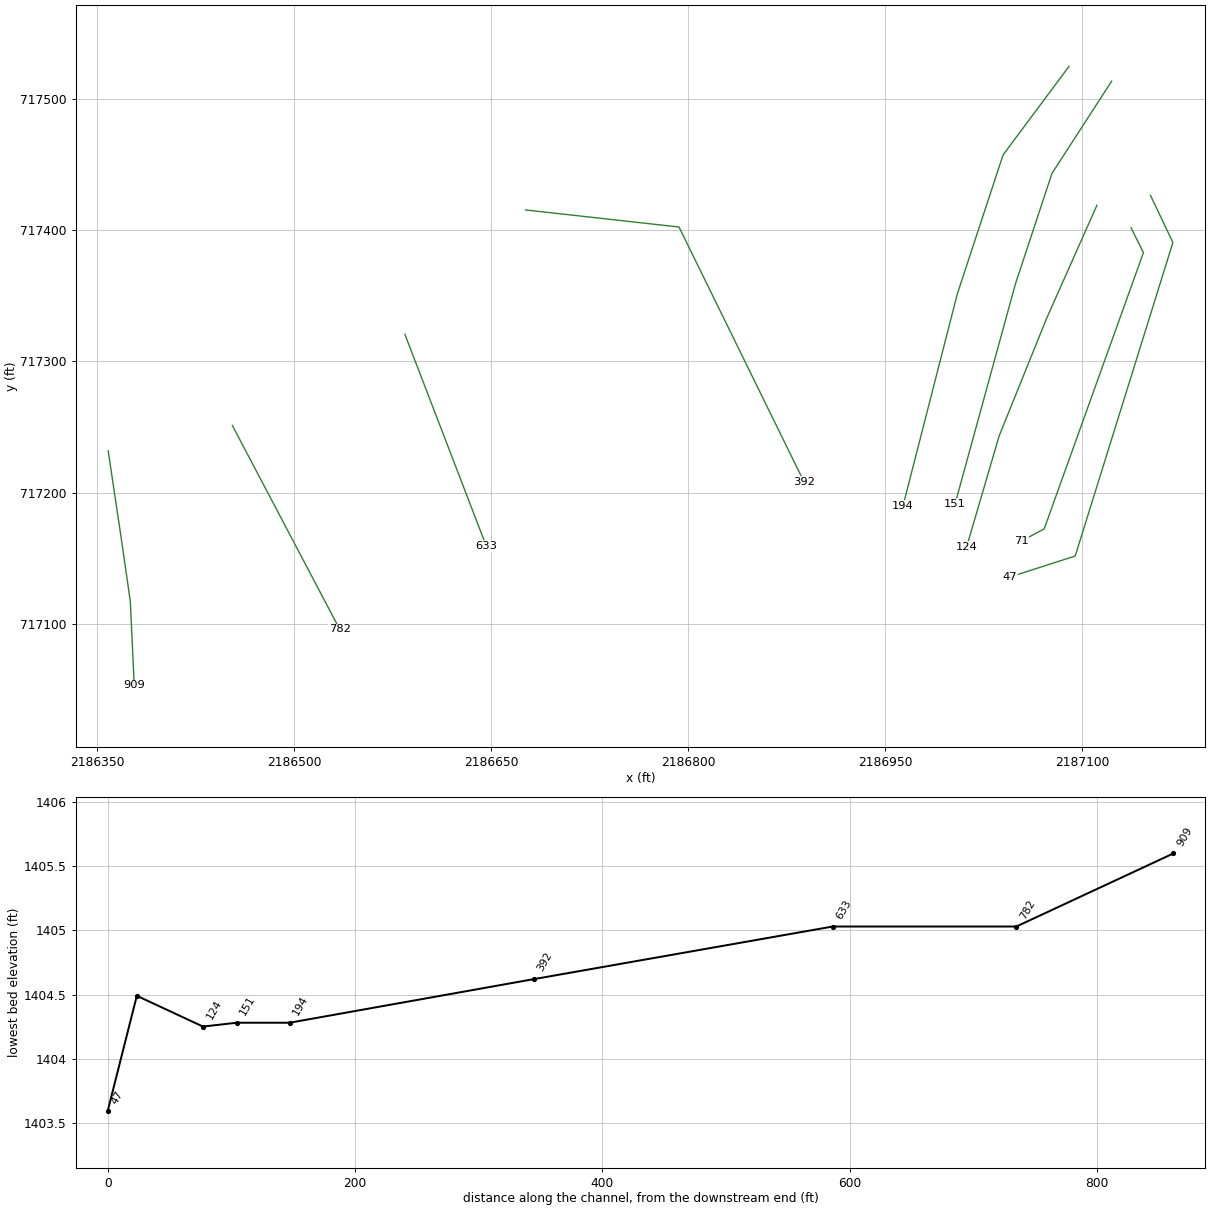
HEC-RAS study STONYRN.prj: STONYRN

--- STONYRN.g01 (geometry) --- (continued)

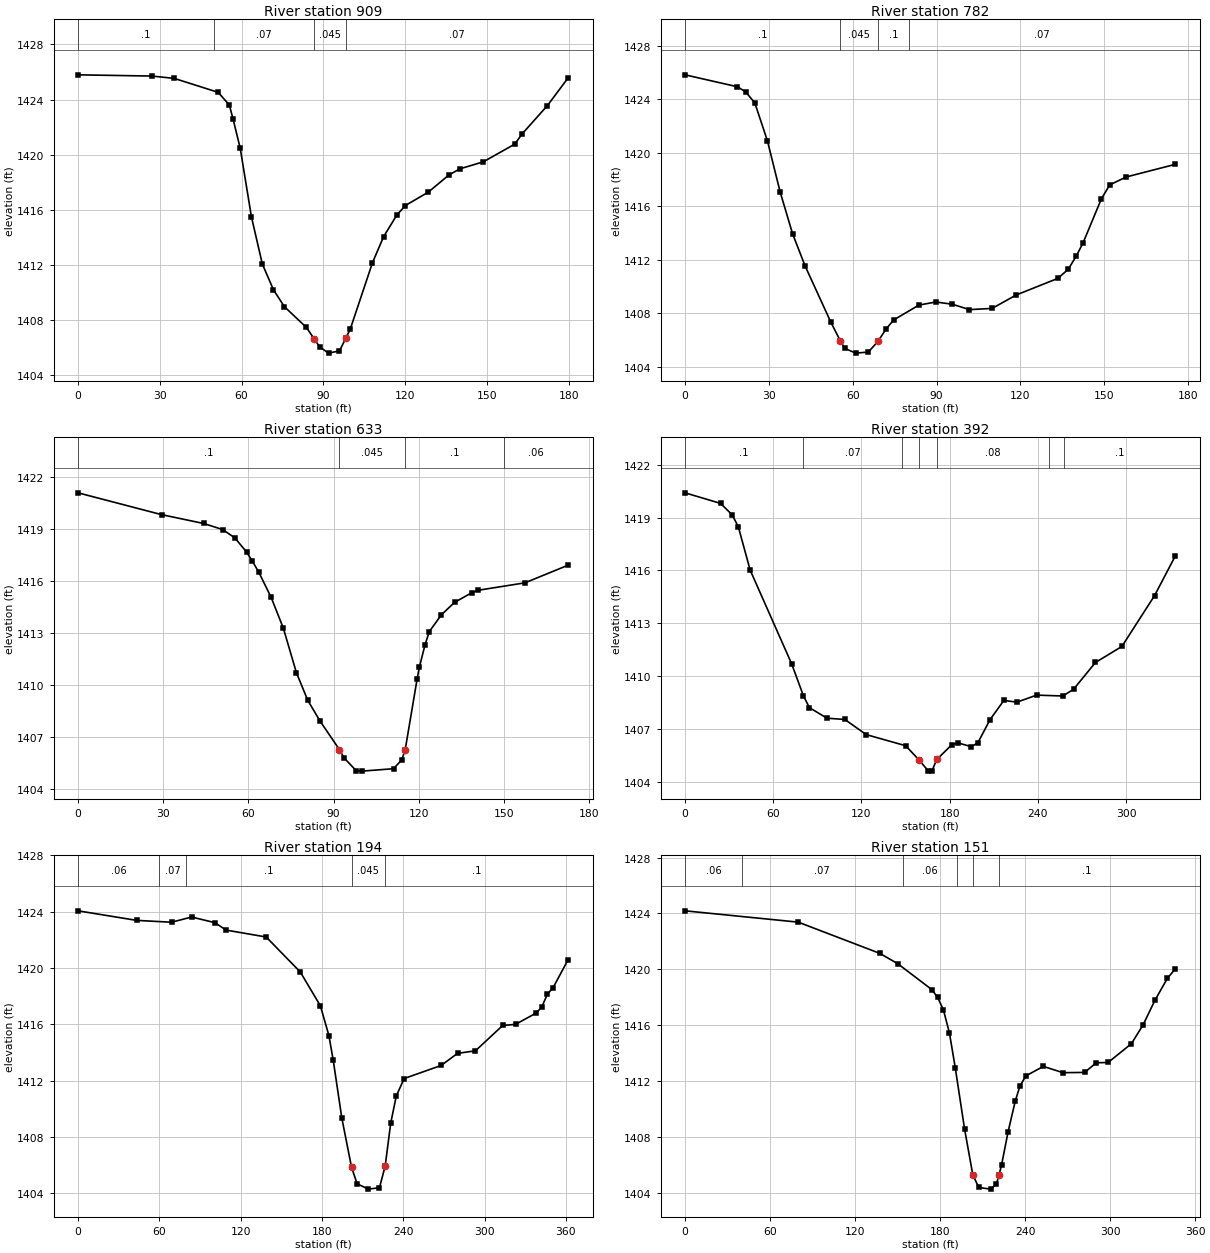
Type RM Length L Ch R = 1 ,909     ,122.6,127,130
XS GIS Cut Line= 4
2186358.33872929717232.0485989592186368.25367124717165.618487875
2186375.19413061717117.5310194052186378.16861319 717053.57964381
#Sta/Elev= 30
       0 1425.79    27.2  1425.7    35.3 1425.53    51.4 1424.52    55.5  1423.6
    56.9 1422.56    59.5 1420.46    63.6  1415.5    67.6 1412.07    71.7 1410.19
    75.7 1408.97    83.8 1407.46    86.6 1406.64    88.7 1406.04    91.9  1405.6
    95.9 1405.76   98.21 1406.67    99.9 1407.36     108 1412.15   112.1 1414.05
     117 1415.63   120.1 1416.31   128.5 1417.28   136.1 1418.53   140.1 1418.97
   148.7 1419.48   160.2 1420.76   162.9  1421.5   172.2 1423.56   179.8 1425.57
#Mann= 4 ,-1,0
       0      .1       0      50     .07       0    86.6    .045       0
   98.21     .07       0
Bank Sta=86.6,98.21
XS Rating Curve= 0 ,0
Exp/Cntr(USF)=0,0
Exp/Cntr=0.3,0.1

Type RM Length L Ch R = 1 ,782     ,148.8,148.5,148.6
XS GIS Cut Line= 2
2186452.92091843717251.2527227342186534.71918954717096.083881174
#Sta/Elev= 30
       0 1425.82    18.7 1424.93    21.7 1424.55      25 1423.71    29.5 1420.88
      34  1417.1    38.5 1413.94      43 1411.53    52.1 1407.38    55.61405.937
    57.2 1405.38    61.1 1405.03    65.6 1405.11    69.1 1405.92      72 1406.85
    74.7 1407.51    83.7 1408.62    89.8 1408.85    95.7 1408.68   101.8 1408.28
   109.9 1408.37   118.5 1409.37   133.5 1410.62   137.2 1411.31   140.1 1412.31
   142.5 1413.29     149 1416.55     152  1417.6   157.9 1418.19   175.4 1419.13
#Mann= 4 ,-1,0
       0      .1       0    55.6    .045       0    69.1      .1       0
      80     .07       0
Bank Sta=55.6,69.1
XS Rating Curve= 0 ,0
Exp/Cntr(USF)=0,0
Exp/Cntr=0.3,0.1

Type RM Length L Ch R = 1 ,633     ,239.1,241.6,243.9
XS GIS Cut Line= 2
 2186584.2938993717320.6573164032186646.26228651717159.539509671
#Sta/Elev= 30
       0 1421.11    29.4 1419.85    44.2 1419.34    50.9 1418.99    55.2 1418.51
    59.4 1417.68    61.4 1417.16    63.7 1416.51      68 1415.07    72.3 1413.29
    76.9 1410.72    80.9 1409.12    85.2 1407.93   92.07 1406.27    93.7 1405.79
      98 1405.05     100 1405.03   111.1 1405.17     114 1405.68   115.2 1406.25
   119.4 1410.34   120.2 1411.03   122.2 1412.33   123.7 1413.09     128 1414.07
   132.6 1414.78   138.8 1415.35   140.9 1415.48   157.4 1415.91   172.6 1416.93
#Mann= 4 ,-1,0
       0      .1       0   92.07    .045       0   115.2      .1       0
     150     .06       0
Bank Sta=92.07,115.2
XS Rating Curve= 0 ,0
Exp/Cntr(USF)=0,0
Exp/Cntr=0.3,0.1

Type RM Length L Ch R = 1 ,392     ,204.7,197.6,188.6
XS GIS Cut Line= 3
2186676.13145869717415.3006541052186793.03799796717402.311038631
2186888.09836575717208.647680652
#Sta/Elev= 30
       0  1420.4    24.2  1419.8    32.2 1419.14    36.3 1418.46    44.3 1416.02
    72.5 1410.71    80.5  1408.9    84.6 1408.22    96.6 1407.62   108.7 1407.55
   123.3 1406.69   150.1 1406.06     159 1405.27   165.6 1404.62   167.9 1404.62
  171.261405.282   181.3  1406.1   185.7 1406.22   194.6 1406.01   199.1 1406.21
   207.5 1407.54   216.9 1408.63   225.8 1408.53   239.2 1408.93     257 1408.88
   264.3 1409.26   279.2 1410.78   297.2 1411.69   319.4 1414.57   333.4  1416.8
#Mann= 7 ,-1,0
       0      .1       0      80     .07       0  147.63     .08       0
     159    .045       0  171.26     .08       0  247.63     .06       0
  257.63      .1       0
Bank Sta=159,171.26
XS Rating Curve= 0 ,0
Exp/Cntr(USF)=0,0
Exp/Cntr=0.3,0.1

Type RM Length L Ch R = 1 ,194     ,42.1,42.8,42.3
XS GIS Cut Line= 4
2187090.02784266717524.5315115022187039.84069197717457.221685863
2187005.00490501717351.5334508682186963.67431032717190.344131574
#Sta/Elev= 30
       0 1424.06    43.3 1423.38      69 1423.25    83.8 1423.62   100.9 1423.22
   109.3 1422.69   138.8  1422.2     164 1419.71   178.8 1417.31   185.1 1415.19
   188.3 1413.43   194.6 1409.34   201.8 1405.83   205.9 1404.66   214.2 1404.28
   222.4 1404.38   226.6 1405.92   230.7 1408.97   234.8  1410.9   240.6 1412.14
   267.9 1413.07     280 1413.93   293.2 1414.11   313.3 1415.91   322.8 1415.99
   338.1  1416.8   342.2 1417.23   346.3 1418.14   350.5  1418.6   361.6 1420.59
#Mann= 5 ,-1,0
       0     .06       0      60     .07       0      80      .1       0
   201.8    .045       0   226.6      .1       0
Bank Sta=201.8,226.6
XS Rating Curve= 0 ,0
Exp/Cntr(USF)=0,0
Exp/Cntr=0.3,0.1

Type RM Length L Ch R = 1 ,151     ,29.1,27.2,25.5
XS GIS Cut Line= 4
2187122.50188135717513.3132072292187077.03822719717443.051196254
2187049.28768504717359.2091327392187003.23359381717191.525005708
#Sta/Elev= 30
       0 1424.19    79.9 1423.38   137.4 1421.15   150.1 1420.41   174.1 1418.56
   178.3    1418   182.4 1417.09   186.6 1415.46   190.7 1412.98   197.3 1408.58
   203.1 1405.31   207.3  1404.4   215.6 1404.28   219.7 1404.62   221.5 1405.26
   223.4    1406     228 1408.38   233.1 1410.59   236.3 1411.63   240.5 1412.38
   252.9 1413.06   266.8 1412.61     282 1412.63   290.3 1413.32   298.6 1413.34
   315.1 1414.69   323.4 1416.05   331.7  1417.8   340.5 1419.37   345.9 1420.02
#Mann= 6 ,-1,0
       0     .06       0      40     .07       0  153.69     .06       0
     192      .1       0   203.1    .045       0   221.5      .1       0
Bank Sta=203.1,221.5
XS Rating Curve= 0 ,0
Exp/Cntr(USF)=0,0
Exp/Cntr=0.3,0.1

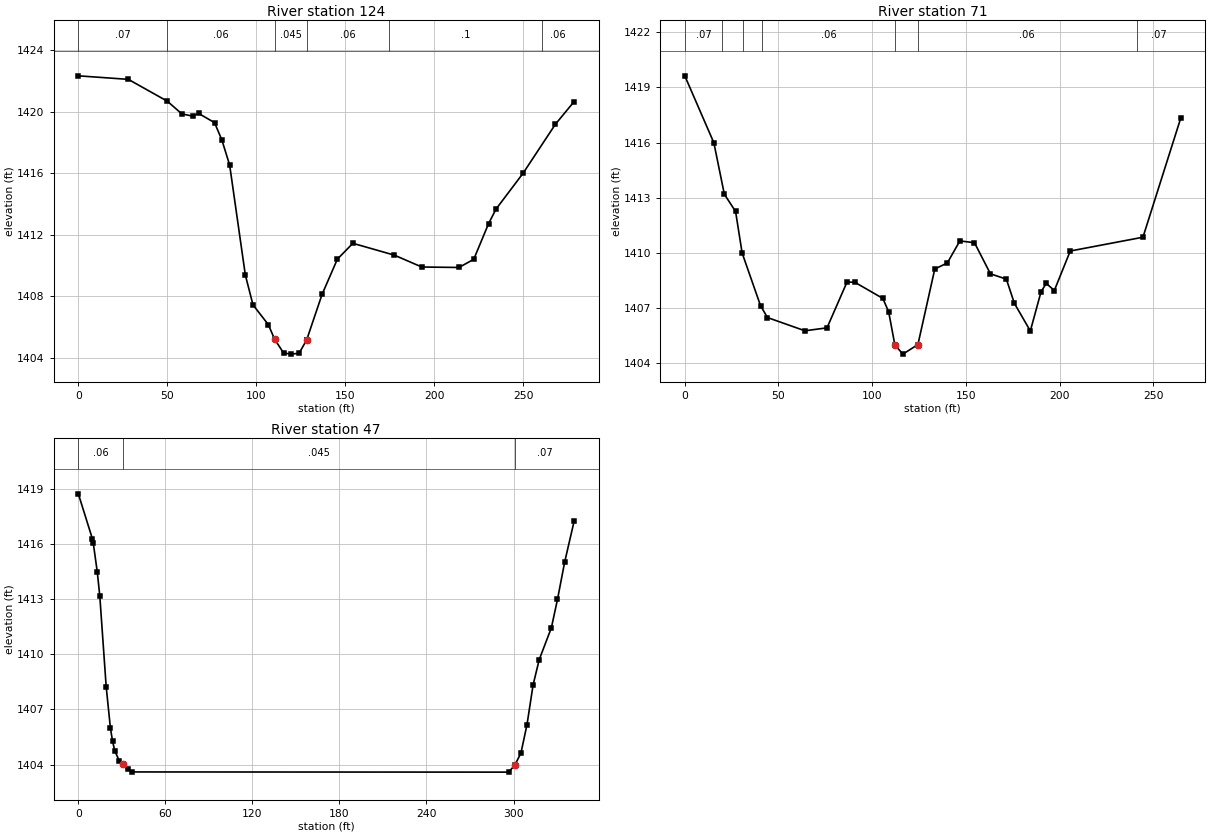
Type RM Length L Ch R = 1 ,124     ,137.4,53.5,133.7
XS GIS Cut Line= 4
2187111.28357708717418.8432765072187072.90516772717332.639464724
2187036.88850663717243.4834676052187012.09014982717159.050967023
#Sta/Elev= 30
       0 1422.33    28.1  1422.1      50 1420.68    58.1 1419.86    64.2 1419.71
    67.5 1419.89    76.5 1419.29    80.6 1418.17      85 1416.53    93.8 1409.39
    98.1 1407.45   106.7 1406.17  110.221405.226   115.3 1404.32   119.7 1404.25
     124 1404.31   128.3 1405.18   128.3 1405.19   136.9 1408.13   145.5 1410.42
   154.2 1411.45   177.5 1410.68   192.9 1409.91   213.8 1409.88   222.1 1410.41
   230.4 1412.72   234.6 1413.67   249.8    1416     268 1419.19   278.5 1420.66
#Mann= 6 ,-1,0
       0     .07       0      50     .06       0  110.22    .045       0
   128.3     .06       0  174.36      .1       0  260.52     .06       0
Bank Sta=110.22,128.3
XS Rating Curve= 0 ,0
Exp/Cntr(USF)=0,0
Exp/Cntr=0.3,0.1

Type RM Length L Ch R = 1 ,71      ,23.6,23.6,23.6
XS GIS Cut Line= 4
2187137.26280802717401.720601564 2187146.7098011717382.826615419
2187071.13385652717172.6310195642187053.42074451717163.184026492
#Sta/Elev= 30
       0 1419.63    15.5 1415.99    21.1 1413.19    27.1 1412.25    30.6 1409.99
    40.4 1407.13    44.1 1406.48    64.1 1405.76    75.9 1405.92    86.6 1408.42
    90.9 1408.39   105.7 1407.52   108.8 1406.79   112.1 1404.99   116.4 1404.49
   124.4 1405.01   133.4 1409.12   140.1 1409.45   146.8 1410.65   154.6 1410.55
   163.1 1408.86   171.6 1408.57   175.9 1407.25   184.4 1405.75   190.1 1407.88
   192.9 1408.34   197.2 1407.95   205.7  1410.1   244.5 1410.85   264.6 1417.31
#Mann= 7 ,-1,0
       0     .07       0      20     .06       0   31.12     .07       0
   41.12     .06       0   112.1    .045       0   124.4     .06       0
  241.12     .07       0
Bank Sta=112.1,124.4
XS Rating Curve= 0 ,0
Exp/Cntr(USF)=0,0
Exp/Cntr=0.3,0.1

Type RM Length L Ch R = 1 ,47      ,,,
XS GIS Cut Line= 4
 2187152.0237347717426.5189583782187169.14640964 717390.50229729
 2187094.7513392717151.9657222192187045.15462557 717136.02392141
#Sta/Elev= 23
       0 1418.74     9.7 1416.29    10.3 1416.06    13.1 1414.46    14.8 1413.17
    19.2 1408.24    22.1    1406    23.6 1405.27    25.1 1404.76    28.1 1404.22
   30.66 1404.01    34.1 1403.74    37.1  1403.6   296.7 1403.59   300.9 1403.98
   305.1 1404.62   309.3 1406.18   313.5 1408.34   317.7 1409.71   326.1 1411.45
   330.3 1412.99   335.3 1415.04   341.8 1417.26
#Mann= 3 ,-1,0
       0     .06       0   30.66    .045       0   300.9     .07       0
Bank Sta=30.66,300.9
XS Rating Curve= 0 ,0
Exp/Cntr(USF)=0,0
Exp/Cntr=0.3,0.1
LCMann Table=0

Chan Stop Cuts=-1
Use User Specified Reach Order=0
Composite Channel Slope=5